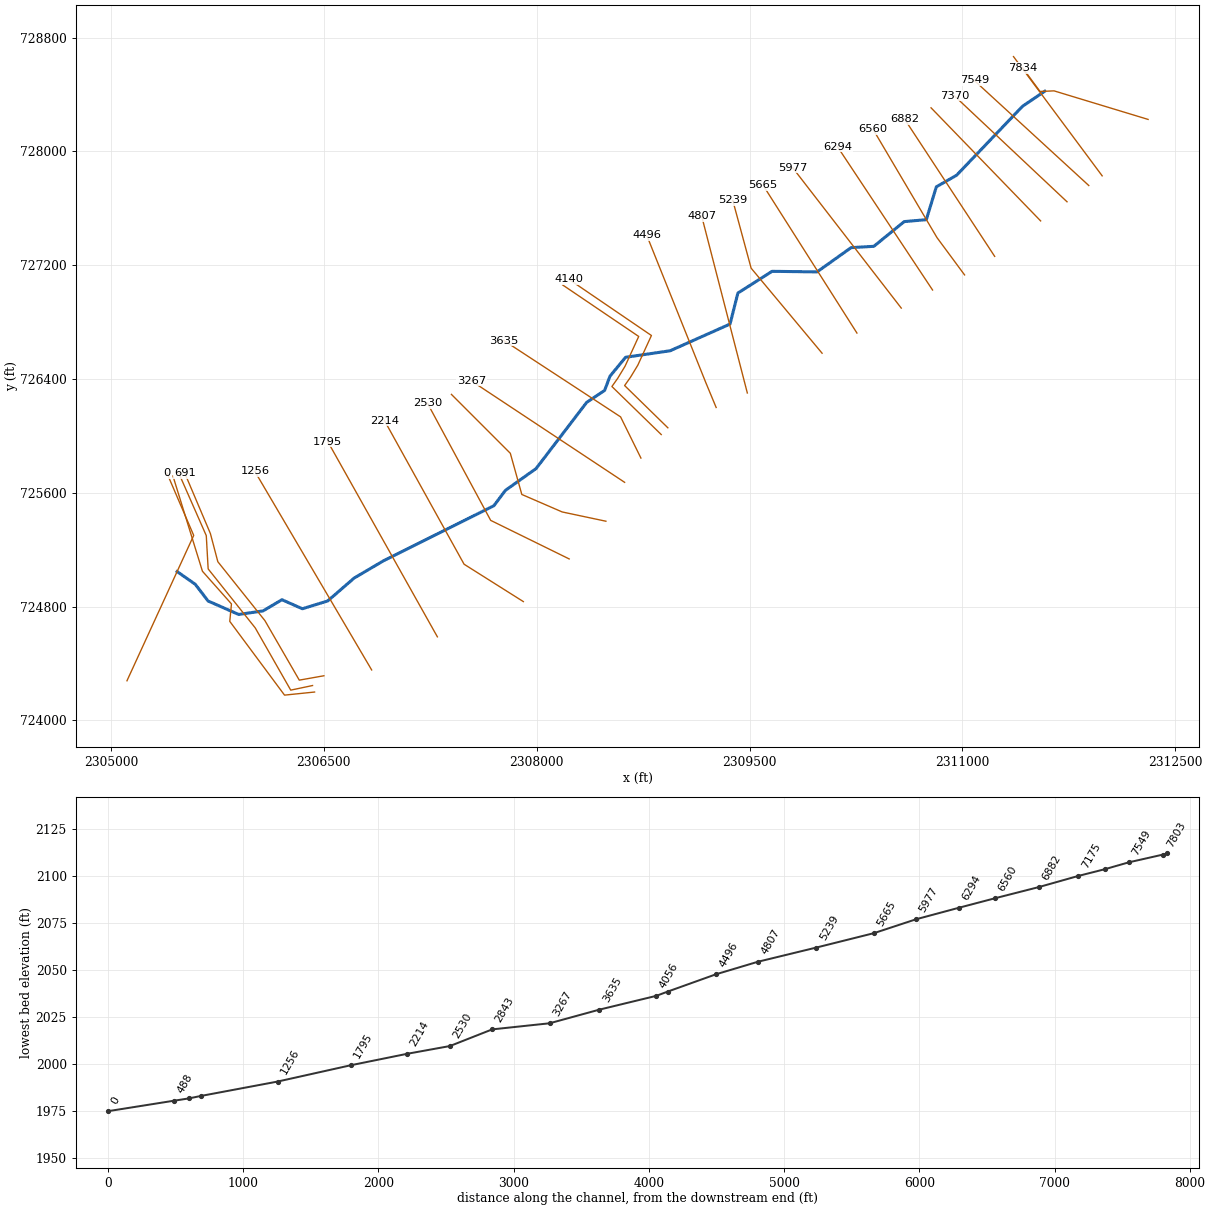
--- LOGLCKRN.prj (project) ---

Proj Title=LOGLCKRN
Current Plan=p01
Default Exp/Contr=0,0
English Units
Geom File=g01
Flow File=f01
Plan File=p01
BEGIN DESCRIPTION:
----------MODEL BY WOOD PLC 2022----------
AFH study
Randolph County, WV
HEC-RAS Version: RAS 6.2
Vertical Datum: NAVD88
Projection: NAD 1983 StatePlane West Virginia S FIPS 4702 (US Feet)
Terrain: 1-meter LIDAR (FEMA Region III 3DEP collected 2016-2018)
Land Use: 2019 NLCD
Hydrologic Method:
WV SIR2010-5033 regression equations
Additional Model Notes:
None
END DESCRIPTION:
DSS Export Rating Curves= 0
DSS Export Rating Curve Sorted= 0
DSS Export Volume Flow Curves= 0
DXF OffsetX= 0
DXF OffsetY= 0
DXF ScaleX= 0
DXF ScaleY= 0

--- LOGLCKRN.p01 (plan) ---

Plan Title=Floodplain
Program Version=6.20
Short Identifier=Floodplain
Geom File=g01
Flow File=f01
Subcritical Flow
K Sum by GR= 0
Std Step Tol= 0.01
Critical Tol= 0.01
Num of Std Step Trials= 20
Max Error Tol= 0.3
Flow Tol Ratio= 0.001
Split Flow NTrial= 30
Split Flow Tol= 0.02
Split Flow Ratio= 0.02
Log Output Level= 0
Friction Slope Method= 1
Unsteady Friction Slope Method= 2
Unsteady Bridges Friction Slope Method= 1
Parabolic Critical Depth
Global Vel Dist= 0 , 0 , 0
Global Log Level= 0
CheckData=True
Encroach Param=-1 ,0,0, 0
Mapping Interval=1HOUR
Computation Time Step Use Courant=        0
Computation Time Step Use Time Series=    0
Computation Time Step Count To Double=0
Computation Time Step Max Doubling=0
Computation Time Step Max Halving=0
Computation Time Step Residence Courant=0
Run HTab= 0
Run UNet= 0
Run Sediment= 0
Run PostProcess= 0
Run WQNet= 0
Run RASMapper=-1
UNET Theta= 0
UNET Theta Warmup= 0
UNET ZTol= 0
UNET ZSATol= 0
UNET MxIter= 0
UNET Max Iter WO Improvement= 0
UNET MaxInSteps= 0
UNET DtIC= 0
UNET DtMin= 0
UNET MaxCRTS= 0
UNET WFStab= 0
UNET SFStab= 0
UNET WFX= 1
UNET SFX= 1
UNET Gravity=32.174
UNET 1D Methodology=Finite Difference
UNET DSS MLevel= 1
UNET Pardiso=0
UNET DZMax Abort= 0
UNET Use Existing IB Tables= 0
UNET Froude Reduction=False
UNET Froude Limit= 0
UNET Froude Power= 0
UNET D1 Cores= 0
UNET WindReference=Eulerian
UNET WindDragFormulation=Hsu (1988)
UNET D2 Coriolis=0
UNET D2 Cores= 0
UNET D2 Theta= 1
UNET D2 Theta Warmup= 1
UNET D2 Z Tol= 0.01
UNET D2 Volume Tol= 0.01
UNET D2 Max Iterations= 20
UNET D2 Equation= 0
UNET D2 RampUpFraction=0.1
UNET D2 TimeSlices= 1
UNET D2 Turbulence Formulation=Non-Conservative (original)
UNET D2 Eddy Viscosity=0.3
UNET D2 Transverse Eddy Viscosity=0.1
UNET D2 Smagorinsky Mixing=0
UNET D2 BCVolumeCheck=0
UNET D2 Cores=0
UNET D2 SolverType=PARDISO (Direct)
UNET D2 Minimum Iterations= 2147483647
UNET D2 Maximum Iterations= 2147483647
UNET D2 Restart Number= 10
UNET D2 Relaxation Coeff=1.3
UNET D2 SOR Precondition Iterations= 10
UNET D2 ILUT Maximum Fill= 8
UNET D2 ILUT Tolerance=1E-08
UNET D1D2 MaxIter= 0
UNET D1D2 ZTol=0.01
UNET D1D2 QTol=0.1
UNET D1D2 MinQTol=1
Write IC File= 0
Write IC File at Fixed DateTime=0
Write IC File at Sim End=0
Echo Input=False
Echo Parameters=False
Echo Output=False
Write Detailed= 0
HDF Write Warmup=0
HDF Write Time Slices=0
HDF Flush=0
HDF Compression= 1
HDF Chunk Size= 1
HDF Spatial Parts= 1
HDF Use Max Rows=0
HDF Fixed Rows= 1
Calibration Method= 0
Calibration Iterations= 20
Calibration Max Change=0.05
Calibration Tolerance=0.2
Calibration Maximum=1.5
Calibration Minimum=0.5
Calibration Optimization Method= 1
WQ AD Non Conservative
WQ ULTIMATE=-1
WQ Max Comp Step=1HOUR
WQ Output Interval=15MIN
WQ Output Selected Increments= 0
WQ Output face flow=0
WQ Output face velocity=0
WQ Output face area=0
WQ Output face dispersion=0
WQ Output cell volume=0
WQ Output cell surface area=0
WQ Output cell continuity=0
WQ Output cumulative cell continuity=0
WQ Output face conc=0
WQ Output face dconc_dx=0
WQ Output face courant=0
WQ Output face peclet=0
WQ Output face adv mass=0
WQ Output face disp mass=0
WQ Output cell mass=0
WQ Output cell source sink temp=0
WQ Output nsm pathways=0
WQ Output nsm derived pathways=0
WQ Create Restart=0
WQ Fixed Restart=0
WQ System Summary=0
WQ Write To DSS=0
Sorting and Armoring Iterations= 10
XS Update Threshold= 0.02
Bed Roughness Predictor= 0
Hydraulics Update Threshold= 0.02
Energy Slope Method= 1
Volume Change Method= 1
Sediment Retention Method= 0
Sediment TS Multiplier= 1
Warm Up Method= 0
XS Weighting Method= 0
Number of US Weighted Cross Sections= 1
Number of DS Weighted Cross Sections= 1
Upstream XS Weight=0
Main XS Weight=1
Downstream XS Weight=0
Number of DS XS's Weighted with US Boundary= 1
Upstream Boundary Weight= 1
Weight of XSs Associated with US Boundary= 0
Number of US XS's Weighted with DS Boundary= 1
Downstream Boundary Weight= 0.5
Weight of XSs Associated with DS Boundary= 0.5
Percentile Method= 0
Sediment Output Level= 3
Mass or Volume Output= 0
Output Increment Type= 1
Profile and TS Output Increment= 1
Transport Output Increment 1
XS Output Flag= 0
XS Output Increment= 10
Read HDF5 Sediment Hotstart= 0
Sediment Hotstart Type= 0
Write Gradation File= 0
Read Gradation Hotstart= 0
Write HDF5 File= 1
Write Binary Output= 1
Write DSS Sediment File= 0
DSS Sediment Output Type= 1
SV Curve= 0
Specific Gage Flag= 0
Subcell Erosion Methods= 0
Subcell Deposition Methods= 0
Advection Scheme= 1
Matrix Solver= 0
Implicit Weighting Factor= 1
Maximum Outer Loop Convergence Iterations= 5
Convergence Maximum Absolute= 0.001
Convergence RMSE= 0.0001
Grain Fractions Max Abs Error= 0.001
Max Subgrid Regions= 1
Max Subgrid Length Scale= 3.402823E+38
Initial Layer Thickness= 3.402823E+38
Min Layer Thickness= 3.402823E+38
Max Layer Thickness= 3.402823E+38
Number of Layers= 5

--- LOGLCKRN.f01 (steady flow) ---

Flow Title=Flow
Program Version=6.20
Number of Profiles= 1
Profile Names=P100yr
River Rch & RM=LOGLCKRN,Main            ,7834
     599
River Rch & RM=LOGLCKRN,Main            ,4140
     711
River Rch & RM=LOGLCKRN,Main            ,0
    1210
Boundary for River Rch & Prof#=LOGLCKRN,Main            , 1
Up Type= 0
Dn Type= 1
Dn Known WS=1980.33
DSS Import GetInterval= 0
DSS Import GetPeak= 0
DSS Import FillOption= 0

--- LOGLCKRN.g01 (geometry) ---

Geom Title=Geometry
Program Version=6.20

River Reach=LOGLCKRN        ,Main
Reach XY= 30
2311579.85000002728422.707000017     2311422.906728316.735000014
2310958.57399999727832.1379999972310815.78099999727750.726999998
2310745.08499998727519.8209999952310589.57199998727506.318000004
2310375.46600002 727332.59800002      2310215.05727323.223000005
2309975.19499999727152.7570000142309658.47099999727156.893000022
2309417.34100002727004.1609999982309362.19399999726786.290999994
     2308940.575 726598.630000012308626.09100004726552.702000007
2308516.64200005726420.4669999932308478.13000003726319.666999996
2308351.78000003726235.5740000012307995.28300002 725770.34800002
2307778.98800002725617.1079999952307698.10500002725509.543000013
2306920.35000001725122.392000005     2306712.932725000.688999996
2306526.99400003724839.9600000082306348.56900001724785.274000019
2306204.59800003724848.8130000082306071.55700003724770.202000007
2305899.65099999724745.1679999982305684.04400004724839.893000007
2305593.32100002724957.8050000072305465.79996239725046.488936991

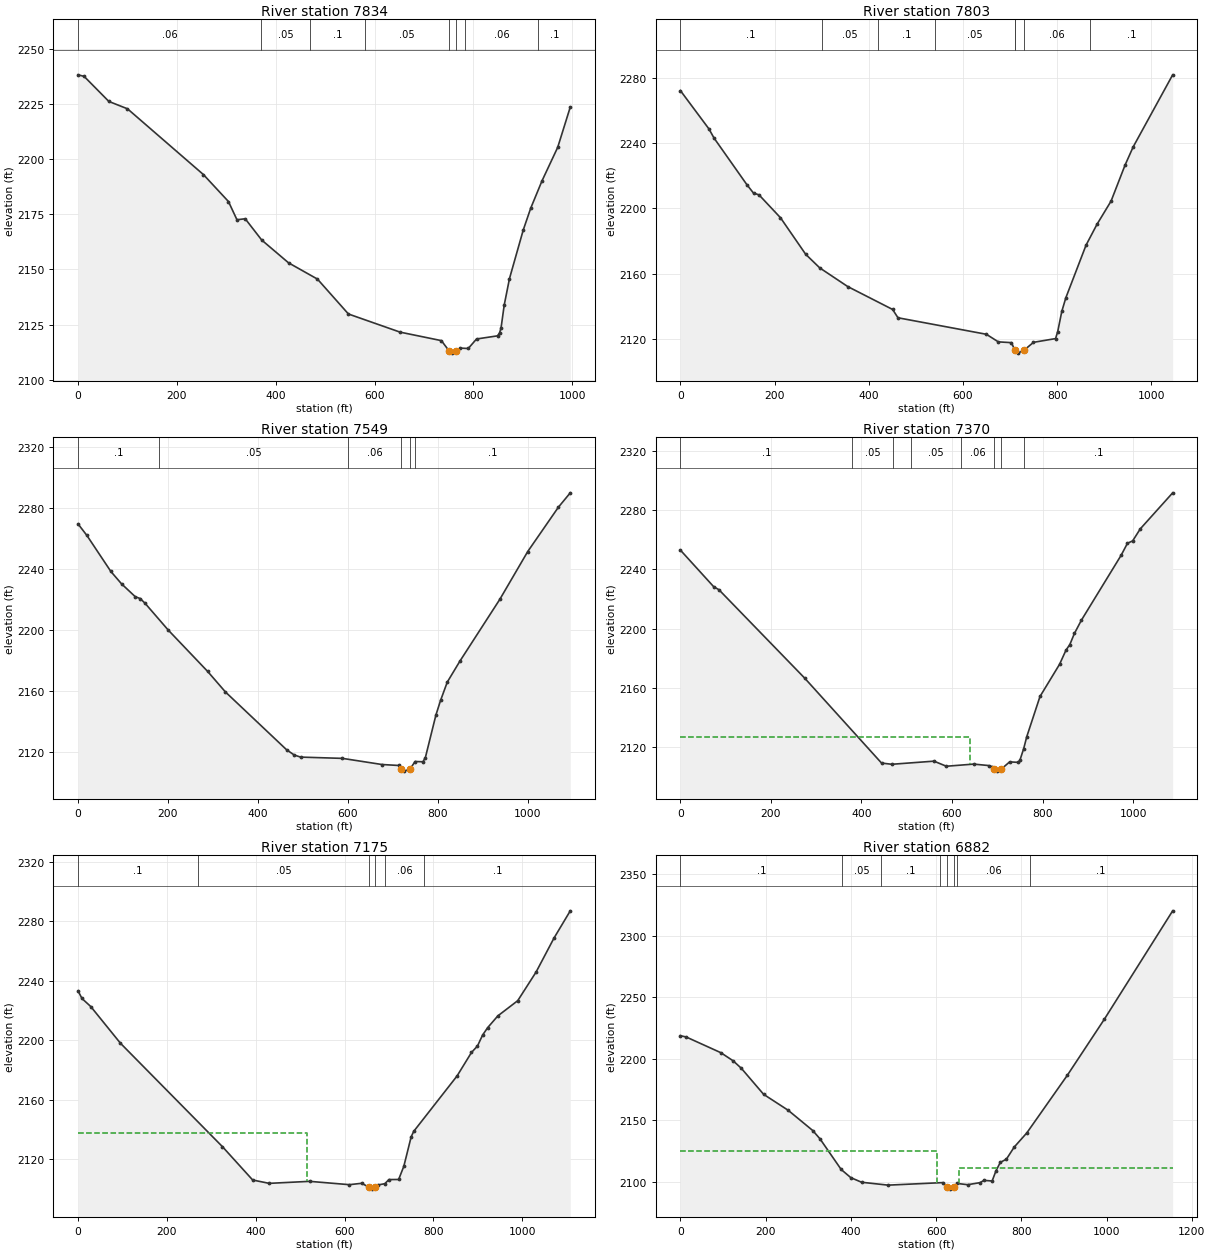
Type RM Length L Ch R = 1 ,7834    ,30.7,30.7,30.7
XS GIS Cut Line= 4
2312307.93701956728224.5452304672311644.97578725728425.215138944
 2311546.4886906728420.9755302692311424.61980542728585.619587063
#Sta/Elev= 30
       0 2238.25    12.3 2237.55    62.4 2226.18   100.1 2222.84   253.8    2193
   304.4 2180.79   321.6 2172.52   338.3 2172.98   371.7 2163.32     426 2152.99
   484.5 2145.61   547.2 2129.78   651.7 2121.56   735.3 2117.71     751 2113.01
   757.5 2112.04   764.6 2112.99   773.5 2114.32   789.6 2114.14   806.4 2118.45
   848.9 2119.88   853.1 2121.26     856 2123.42   862.4 2133.82   873.1 2145.88
     901 2167.93     916 2177.74   938.9 2190.18   970.7 2205.39996.0848 2223.63
#Mann= 8 ,-1,0
       0     .06       0     370     .05       0     470      .1       0
     580     .05       0     751    .045       0   764.6     .05       0
  782.67     .06       0  931.24      .1       0
Bank Sta=751,764.6
XS Rating Curve= 0 ,0
Exp/Cntr(USF)=0,0
Exp/Cntr=0.3,0.1

Type RM Length L Ch R = 1 ,7803    ,253.8,253.8,253.8
XS GIS Cut Line= 2
 2311984.3081724 727827.924420092311359.50660639  728666.0728623
#Sta/Elev= 30
       0 2272.04    60.5 2248.63    71.4 2243.01   141.3 2214.42   155.3 2209.31
   166.8 2208.29   212.5 2194.27     266 2171.92   295.9 2163.58   355.4 2152.15
   450.6 2138.16     462 2133.07   649.8 2122.97   675.1 2118.33     703 2117.85
     710 2113.36  710.282113.232   716.3 2111.44   729.7  2113.2   749.8 2118.05
   796.7 2120.33   801.3 2124.67   809.9 2136.95   818.5  2145.3   861.4 2177.48
   884.6 2190.21   914.6 2204.47   944.2 2226.43   961.4 2237.55  1045.4  2281.7
#Mann= 8 ,-1,0
       0      .1       0     300     .05       0     420      .1       0
     540     .05       0     710     .06       0  710.28    .045       0
   729.7     .06       0     870      .1       0
Bank Sta=710.28,729.7
XS Rating Curve= 0 ,0
Exp/Cntr(USF)=0,0
Exp/Cntr=0.3,0.1

Type RM Length L Ch R = 1 ,7549    ,179.3,179.3,179.3
XS GIS Cut Line= 2
 2311890.0726843727759.8876875152311082.40236726728498.982222917
#Sta/Elev= 30
       0 2269.66    19.7 2262.09      73 2238.44    96.7 2230.32   127.3 2221.85
   138.2 2220.65     149 2217.57   200.4 2200.02   288.2 2172.82   327.8 2159.31
   463.7 2121.39   480.7 2117.92   494.9 2116.52   588.2 2115.68   676.1 2111.65
   712.9 2111.03  719.162108.702   724.8 2107.31   738.4 2108.73   749.7 2113.62
   767.1 2113.46   772.5 2116.17   795.9 2144.07   806.3 2153.73   821.3 2165.81
   849.2 2179.48   938.1 2220.12  1000.2 2251.52  1068.4 2280.64  1094.8 2290.07
#Mann= 6 ,-1,0
       0      .1       0     180     .05       0     600     .06       0
  719.16    .045       0   738.4     .06       0     750      .1       0
Bank Sta=719.16,738.4
XS Rating Curve= 0 ,0
Exp/Cntr(USF)=0,0
Exp/Cntr=0.3,0.1

Type RM Length L Ch R = 1 ,7370    ,195,195,195
XS GIS Cut Line= 2
 2311736.6581986727645.6634337072310943.47810302728389.708479122
#Sta/Elev= 30
       0 2252.99    73.6 2228.23    84.9 2226.28   274.1 2166.61   444.3 2109.07
     467 2108.25   560.1 2110.36   587.5 2106.92     648 2108.37   680.7  2107.4
   687.7 2106.71  692.532104.863     699 2103.62   708.2 2104.83   727.3 2109.87
   746.5 2109.55   749.9 2110.87   758.4 2118.88   765.2 2126.96   794.4 2154.09
   837.6 2175.82   851.8 2185.41   860.3 2189.17   870.4 2196.67   885.7 2205.57
   973.5 2249.45   987.6 2257.63   999.1 2259.25  1015.9 2267.36  1087.5 2291.73
#Mann= 8 ,-1,0
       0      .1       0     380     .05       0     470     .06       0
     510     .05       0     620     .06       0  692.53    .045       0
   708.2     .06       0     760      .1       0
#XS Ineff= 2 , 0
          639.01 2126.42
Permanent Ineff=
       F       F
Bank Sta=692.53,708.2
XS Rating Curve= 0 ,0
Exp/Cntr(USF)=0,0
Exp/Cntr=0.3,0.1

Type RM Length L Ch R = 1 ,7175    ,293.2,293.2,293.2
XS GIS Cut Line= 2
2311550.71750583727511.1053773212310778.60500149728306.076475537
#Sta/Elev= 30
       0 2233.29     8.9 2228.14    28.7 2222.72    95.5 2198.08   325.2 2128.56
   393.2 2106.18   430.4 2103.94   521.5 2105.29   610.7 2103.05   638.6 2103.98
   655.3 2101.32   662.4 2100.06   669.6 2101.28   675.4 2102.89   690.6  2103.7
   699.9 2106.47   721.8 2106.55   733.4 2115.33     750 2135.19   755.7 2138.85
   853.3 2176.08   885.8 2191.88   899.3 2196.22   910.8 2203.56   922.2 2208.54
   945.2 2216.47   989.9 2226.67  1031.3 2245.95  1071.5 2268.71  1108.2 2287.04
#Mann= 6 ,-1,0
       0      .1       0     270     .05       0   655.3    .045       0
   669.6     .05       0     690     .06       0     780      .1       0
#XS Ineff= 2 , 0
          515.52 2137.59
Permanent Ineff=
       F       F
Bank Sta=655.3,669.6
XS Rating Curve= 0 ,0
Exp/Cntr(USF)=0,0
Exp/Cntr=0.3,0.1

Type RM Length L Ch R = 1 ,6882    ,322.1,322.1,322.1
XS GIS Cut Line= 2
2311226.81798082727262.0006089522310591.85703976728227.141239375
#Sta/Elev= 30
       0 2218.77    13.4 2217.77    94.8    2205   123.5 2198.44   142.7  2192.4
   195.3 2171.14   252.8 2158.22   310.5 2141.75   327.7 2134.92   377.3 2110.07
   399.9 2103.45   425.2 2099.71   487.4 2097.36   616.5 2099.43   626.2 2095.61
   633.8 2094.12  641.282095.648   650.2  2098.7   674.2 2097.72   703.1 2099.38
   712.4 2101.22   731.6 2100.74   740.6 2109.01   750.7 2115.82   765.1  2118.5
   783.5 2128.34     813 2139.82   908.2 2186.71   994.8 2232.11  1155.3 2320.27
#Mann= 8 ,-1,0
       0      .1       0     380     .05       0     470      .1       0
     610     .05       0   626.2    .045       0  641.28     .05       0
     650     .06       0     820      .1       0
#XS Ineff= 2 , 0
          601.02 2125.33  653.92         2111.35
Permanent Ineff=
       F       F
Bank Sta=626.2,641.28
XS Rating Curve= 0 ,0
Exp/Cntr(USF)=0,0
Exp/Cntr=0.3,0.1

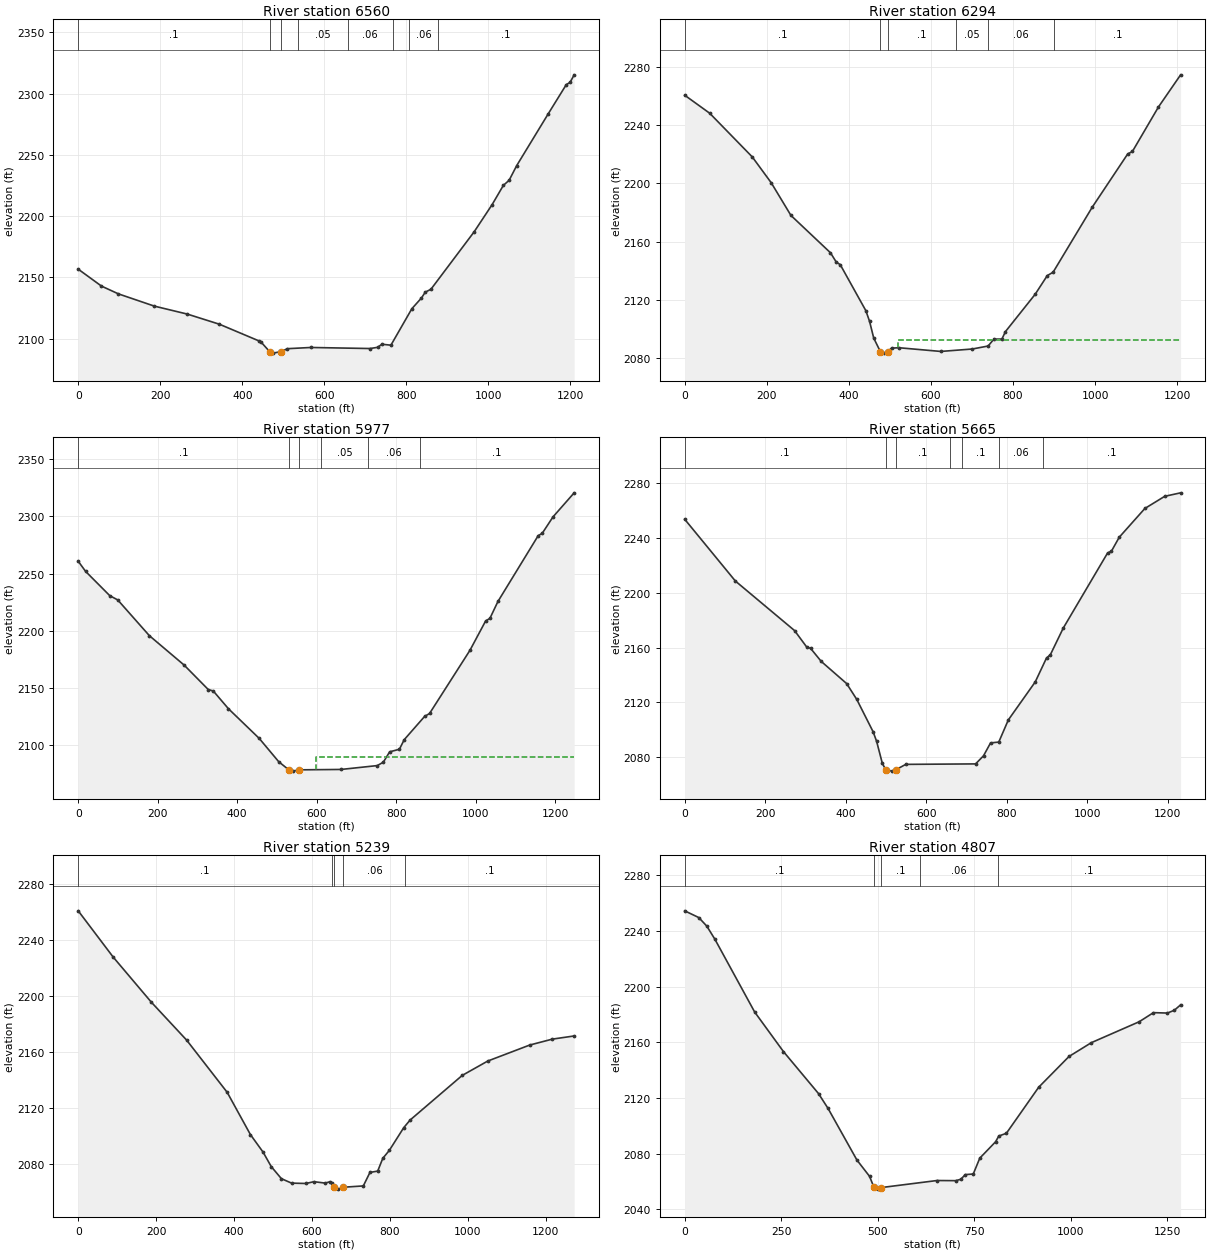
Type RM Length L Ch R = 1 ,6560    ,265.9,265.9,265.9
XS GIS Cut Line= 3
2311014.64614013 727131.64068792 2310820.0989854727394.206182579
2310370.66161148728153.720504405
#Sta/Elev= 30
       0 2156.72    56.7  2142.9    98.2 2136.53   185.6 2126.57   266.2 2120.05
   344.2 2111.81   439.9  2098.3   446.4 2097.04  467.042089.364   474.3 2088.22
  495.05 2089.43   509.9 2091.84   567.3 2092.83   711.4 2091.97     730 2092.95
   740.6 2095.47   762.5  2094.7   813.6 2124.47   836.9 2133.17   846.2 2137.94
   860.1 2140.33   965.5 2187.21  1009.3 2209.38  1036.7 2225.08  1050.7  2229.2
  1069.2 2241.18  1146.5 2283.67  1190.1 2307.24  1199.4 2309.07  1209.3 2315.24
#Mann= 8 ,-1,0
       0      .1       0  467.04    .045       0  495.05      .1       0
  536.79     .05       0  656.79     .06       0  766.79      .1       0
  806.79     .06       0  876.79      .1       0
Bank Sta=467.04,495.05
XS Rating Curve= 0 ,0
Exp/Cntr(USF)=0,0
Exp/Cntr=0.3,0.1

Type RM Length L Ch R = 1 ,6294    ,316.6,316.6,316.6
XS GIS Cut Line= 2
2310789.05365963727025.6258958612310119.88107161728031.724542177
#Sta/Elev= 30
       0  2260.7    60.9  2248.3   164.8 2218.18   210.9 2200.42   258.9 2177.95
   355.2 2152.26   369.4 2145.81     379 2144.09   441.4 2112.41   450.4 2105.12
   460.6 2093.53  476.872084.168   485.5 2083.19  494.342084.182   503.9 2086.63
   522.5 2086.89     624 2084.35   700.8 2086.03   739.3 2088.08   753.3 2092.82
   772.9 2092.88   781.6 2098.04   853.9 2123.68   883.4 2136.54   897.6 2138.86
   992.8 2183.55  1079.3 2220.23  1090.9    2222  1154.3 2252.59  1208.3 2274.72
#Mann= 6 ,-1,0
       0      .1       0  476.87    .045       0  494.34      .1       0
     660     .05       0     740     .06       0     900      .1       0
#XS Ineff= 2 , 0
                          519.75         2092.16
Permanent Ineff=
       F       F
Bank Sta=476.87,494.34
XS Rating Curve= 0 ,0
Exp/Cntr(USF)=0,0
Exp/Cntr=0.3,0.1

Type RM Length L Ch R = 1 ,5977    ,312.6,312.6,312.6
XS GIS Cut Line= 2
2310568.56291258726898.4848851362309803.64837424727884.714232027
#Sta/Elev= 30
       0 2260.77    18.6 2251.87    79.3 2230.66    99.6 2226.86     179 2195.64
   266.6 2169.87   327.2 2148.51     340 2147.18     378 2131.71   455.5 2105.73
   504.6 2085.32   529.9 2078.24     540 2077.08  556.372078.205   661.5 2078.55
   752.6 2081.93   767.8 2084.88   783.8 2093.98   808.3 2096.21   820.4 2104.58
   871.7 2124.92   884.2 2127.51   985.8 2182.78  1025.3 2208.49  1036.1 2210.76
  1056.3 2225.55  1157.6 2283.13  1167.7 2285.16    1195 2299.62  1248.1 2320.62
#Mann= 6 ,-1,0
       0      .1       0   529.9    .045       0  556.37      .1       0
     610     .05       0     730     .06       0     860      .1       0
#XS Ineff= 2 , 0
                          599.29         2089.53
Permanent Ineff=
       F       F
Bank Sta=529.9,556.37
XS Rating Curve= 0 ,0
Exp/Cntr(USF)=0,0
Exp/Cntr=0.3,0.1

Type RM Length L Ch R = 1 ,5665    ,425.9,425.9,425.9
XS GIS Cut Line= 2
 2310256.2024788726723.0012640962309594.64273519727762.193600281
#Sta/Elev= 30
       0 2253.72   125.9 2208.57   272.9 2172.38   302.9 2160.43   312.9 2159.33
   339.2 2149.84   402.3 2133.65   427.5 2122.06   468.1 2098.42   476.8 2091.41
     491 2075.32  499.492070.653   514.7 2069.68   524.2 2070.63   549.2 2074.62
   722.6 2074.96   742.3 2080.88   759.8  2090.3   780.2 2090.91   803.9 2107.07
   870.8 2134.87   898.8 2152.36   908.3  2154.7   940.3 2174.15  1050.5 2229.07
    1060 2230.35  1079.4 2240.55  1143.1 2261.58  1192.4 2270.46  1231.9 2273.01
#Mann= 7 ,-1,0
       0      .1       0  499.49    .045       0   524.2      .1       0
     660     .06       0     690      .1       0     780     .06       0
     890      .1       0
Bank Sta=499.49,524.2
XS Rating Curve= 0 ,0
Exp/Cntr(USF)=0,0
Exp/Cntr=0.3,0.1

Type RM Length L Ch R = 1 ,5239    ,432,432,432
XS GIS Cut Line= 3
 2310010.7311112726581.2234689412309510.66757851727179.065760538
2309381.46652755727655.006003481
#Sta/Elev= 30
       0 2261.04    89.8 2227.94   187.7 2195.69   278.3 2168.56   382.3 2131.24
   441.9 2101.03   474.5 2088.44   495.3 2078.15   521.4  2069.5   547.5 2066.33
   583.9 2066.06   604.9 2067.35   633.7 2066.35   646.6 2067.37   651.8 2066.16
     657 2063.24   667.4 2062.03   680.5 2063.39   731.6 2064.32   748.6 2073.97
   768.5 2074.93   781.6 2084.08   798.2 2089.68   835.3 2105.97   851.6 2111.42
   985.3 2143.33    1051 2153.64  1158.8 2165.08  1216.7  2169.3  1272.6 2171.56
#Mann= 5 ,-1,0
       0      .1       0     650     .06       0     657    .045       0
   680.5     .06       0  839.41      .1       0
Bank Sta=657,680.5
XS Rating Curve= 0 ,0
Exp/Cntr(USF)=0,0
Exp/Cntr=0.3,0.1

Type RM Length L Ch R = 1 ,4807    ,310.3,310.3,310.3
XS GIS Cut Line= 2
2309483.89992468726301.7570386162309162.26651345727544.886878848
#Sta/Elev= 30
       0  2254.4    36.6 2249.55    57.2 2243.44    78.1 2234.06   181.2 2181.71
   255.6 2153.34   346.5 2123.13   371.3 2112.42     446 2075.37   478.7 2063.66
   490.1 2055.71   499.3 2054.48   507.6 2055.55   653.6 2060.67   701.8 2060.56
   714.9 2061.55   726.6 2064.91   747.2 2065.34   764.1 2076.74   805.1 2088.53
   813.3 2092.62     833 2094.61   916.6 2127.67   995.1 2149.77    1053  2159.7
  1176.9 2174.73  1213.8 2181.26  1249.9 2180.96  1267.8 2182.97  1284.1 2186.86
#Mann= 5 ,-1,0
       0      .1       0   490.1    .045       0   507.6      .1       0
     610     .06       0     810      .1       0
Bank Sta=490.1,507.6
XS Rating Curve= 0 ,0
Exp/Cntr(USF)=0,0
Exp/Cntr=0.3,0.1

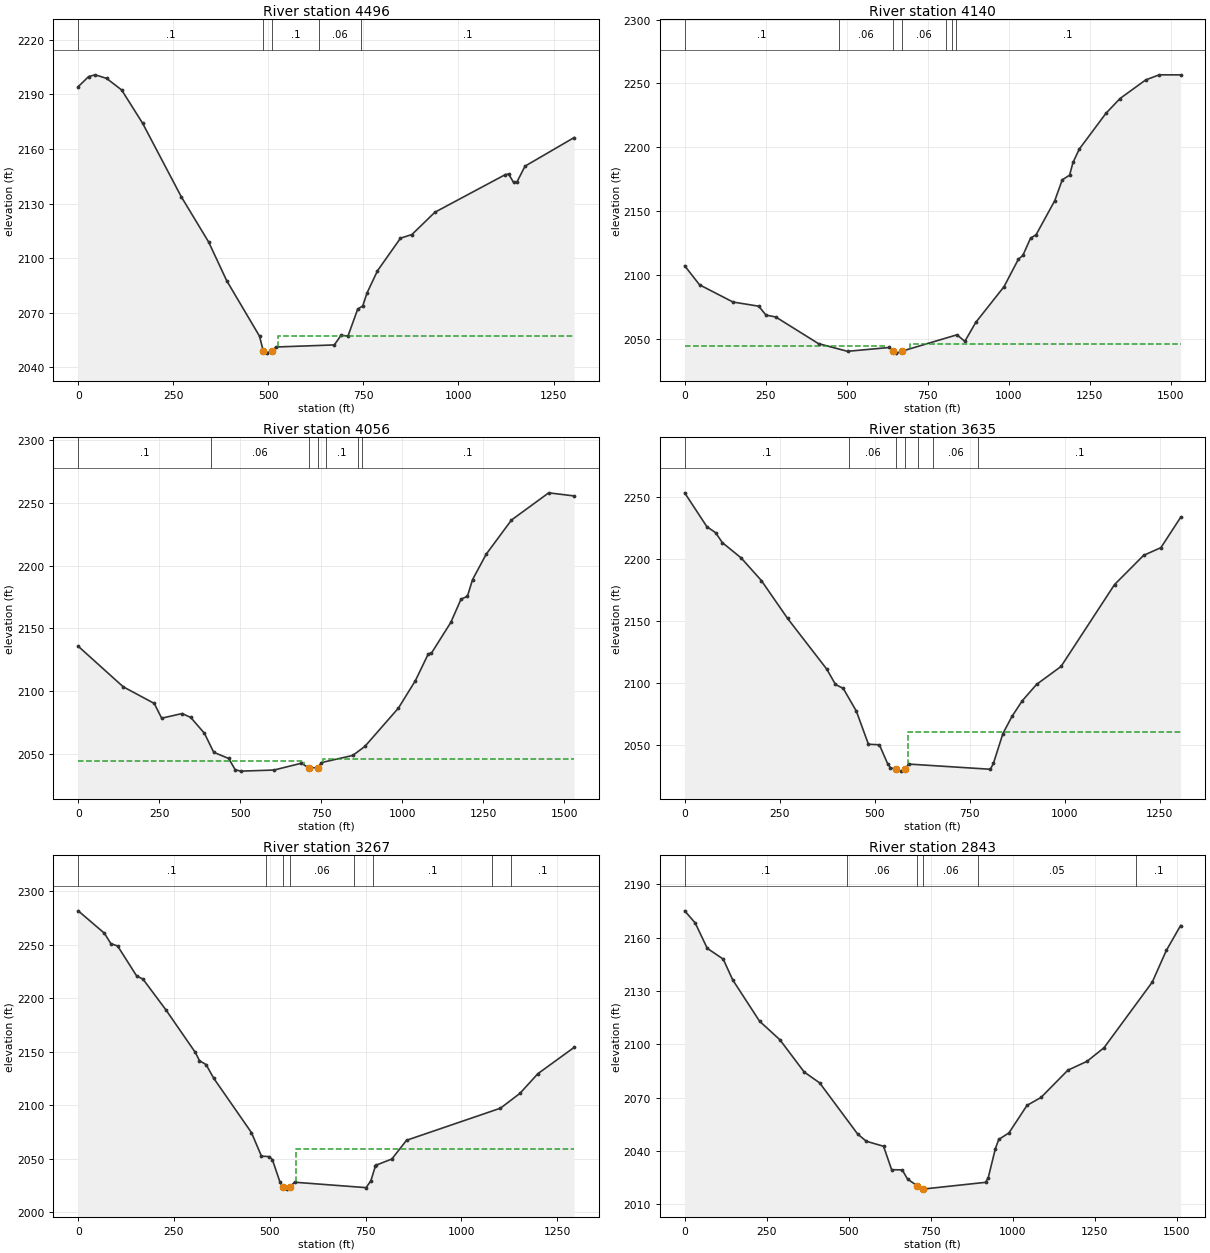
Type RM Length L Ch R = 1 ,4496    ,356.1,356.1,356.1
BEGIN DESCRIPTION:
Structure XS 4
END DESCRIPTION:
XS GIS Cut Line= 3
2309264.27486129726199.7765628632309190.13859866726377.743310905
2308775.54133124727409.010463476
#Sta/Elev= 30
       0 2194.26    27.5 2199.83    44.9 2200.77    74.6 2198.81   114.2 2192.46
   169.4 2174.15   270.7  2133.9   343.1 2108.86   390.5 2087.64   476.8 2057.15
   486.72049.056   495.2 2047.82  510.572049.132   519.8 2051.19   673.6 2052.33
   691.3 2057.65   709.5 2057.21   735.1 2072.04   748.3 2073.76   759.7 2080.95
   787.1 2093.08   847.5 2110.98   877.7 2113.01     938 2125.24  1123.4 2145.95
    1132 2146.24  1144.9 2141.67  1153.6 2141.78  1175.1 2150.58  1304.3  2166.3
#Mann= 5 ,-1,0
       0      .1       0   486.7    .045       0  510.57      .1       0
  632.79     .06       0  742.79      .1       0
#XS Ineff= 2 , 0
                           524.7          2057.1
Permanent Ineff=
       F       F
Bank Sta=486.7,510.57
XS Rating Curve= 0 ,0
Exp/Cntr(USF)=0,0
Exp/Cntr=0.5,0.3

Type RM Length L Ch R = 1 ,4140    ,84.3,84.3,84.3
BEGIN DESCRIPTION:
Structure XS 3 23.3ft
END DESCRIPTION:
XS GIS Cut Line= 6
2308923.90768242726057.1710495362308619.30450499726353.957511957
2308660.03851928726411.355441185 2308711.8818102726496.526561977
2308808.16220761726705.7512717462308225.48459035727101.759445199
#Sta/Elev= 30
       0 2107.08    45.9 2092.17     149 2078.69   228.6 2075.41   250.9 2068.43
   280.9 2066.99   412.9 2046.08   502.5 2040.07   631.3 2043.08  642.352040.244
   653.4 2038.65   670.9 2040.23   840.2 2053.01   864.4 2047.88   898.2 2062.76
   985.3 2090.71  1029.7 2112.25  1043.3 2115.14  1067.1 2128.67  1084.4 2131.46
    1142 2158.16    1165 2174.42  1187.6 2178.05  1198.1 2187.99  1217.4 2198.44
  1299.6 2226.47  1343.2 2238.11  1422.4 2252.67  1464.1 2256.67  1530.2 2256.64
#Mann= 7 ,-1,0
       0      .1       0  475.28     .06       0  642.35    .045       0
   670.9     .06       0  805.37      .1       0  825.69     .06       0
  835.69      .1       0
#XS Ineff= 2 , 0
          619.05  2044.5   694.2          2046.1
Permanent Ineff=
       F       F
Bank Sta=642.35,670.9
XS Rating Curve= 0 ,0
Exp/Cntr(USF)=0,0
Exp/Cntr=0.5,0.3

Type RM Length L Ch R = 1 ,4056    ,420.8,420.8,420.8
BEGIN DESCRIPTION:
Structure XS 2 43.8ft 14.6
END DESCRIPTION:
XS GIS Cut Line= 6
2308877.30411528726009.6729967582308529.72545206726347.286170691
2308570.45946635726404.6840999192308622.30275727726489.855220711
2308718.58315468 726699.07993048 2308183.1785718727060.707715291
#Sta/Elev= 30
       0 2135.79   139.1 2103.49   234.7 2090.28   257.6 2078.52   320.8 2082.22
   347.3 2079.14   389.7 2066.49   418.4 2051.36   464.4 2046.47   484.6 2037.54
   501.6 2036.38   604.4 2037.24   689.1 2042.68   711.1 2039.03  739.922039.032
   750.8 2043.19   847.6 2048.87     885 2056.06   988.8 2086.65  1040.9 2108.38
  1080.9 2129.77  1090.6 2130.36  1150.4 2154.81  1181.7 2173.22  1201.6  2175.6
  1217.4 2188.84  1259.5 2209.04  1337.6 2236.28  1452.6 2257.93  1531.1 2255.45
#Mann= 7 ,-1,0
       0      .1       0     410     .06       0   711.1    .045       0
  739.92     .06       0  764.65      .1       0  864.65     .06       0
  874.65      .1       0
#XS Ineff= 2 , 0
           696.5  2044.5  754.52          2046.1
Permanent Ineff=
       F       F
Bank Sta=711.1,739.92
XS Rating Curve= 0 ,0
Exp/Cntr(USF)=0,0
Exp/Cntr=0.5,0.3

Type RM Length L Ch R = 1 ,3635    ,368.5,368.5,368.5
BEGIN DESCRIPTION:
Structure XS 1
END DESCRIPTION:
XS GIS Cut Line= 3
2308734.11992862725844.3412803012308590.88876676726133.862565364
2307768.66225322726670.400205553
#Sta/Elev= 30
       0 2253.31    58.5 2225.97    81.3 2221.22    99.1  2213.2   148.4 2200.91
   201.8 2182.63   270.8 2152.08     374 2111.17   396.7 2098.91   417.2 2095.69
   451.7  2077.4   483.4 2050.73   512.3 2050.27     534 2035.03   541.3 2031.86
   555.5 2030.39   570.2 2029.06  580.192030.396     589 2034.75   804.3 2030.56
   812.2 2035.23   837.3 2059.37   861.2 2073.21   888.1 2085.71   925.8 2098.94
   990.2  2113.4  1130.9 2179.38  1207.4 2202.93  1252.9 2209.13  1304.8 2233.53
#Mann= 7 ,-1,0
       0      .1       0  433.01     .06       0   555.5    .045       0
  580.19     .06       0  613.01     .05       0  653.01     .06       0
  773.01      .1       0
#XS Ineff= 2 , 0
                          587.22         2060.59
Permanent Ineff=
       F       F
Bank Sta=555.5,580.19
XS Rating Curve= 0 ,0
Exp/Cntr(USF)=0,0
Exp/Cntr=0.3,0.1

Type RM Length L Ch R = 1 ,3267    ,424.2,424.2,424.2
XS GIS Cut Line= 2
2308619.34549272725673.8471214842307539.04089024726387.219206253
#Sta/Elev= 30
       0 2281.66    68.2  2260.8    85.3 2250.99   102.9 2248.84   152.4 2220.93
   169.3 2217.82   229.9  2188.7   305.8 2149.39   316.5 2141.76   333.8 2138.07
     354  2125.2   452.2 2074.61   478.3 2052.64   498.4 2052.14   506.9  2049.3
   526.3  2028.8  534.352023.683   544.6  2021.8  552.242023.644   564.6 2028.25
   751.6 2023.19     764 2029.68   775.5 2042.99   778.4 2044.28   818.7 2049.93
     857  2067.4  1102.2 2097.37    1153 2111.19  1199.9 2129.59  1294.6 2154.15
#Mann= 8 ,-1,0
       0      .1       0     490     .06       0  534.35    .045       0
  552.24     .06       0     720     .05       0     770      .1       0
    1080     .05       0    1130      .1       0
#XS Ineff= 2 , 0
                          568.23         2059.61
Permanent Ineff=
       F       F
Bank Sta=534.35,552.24
XS Rating Curve= 0 ,0
Exp/Cntr(USF)=0,0
Exp/Cntr=0.3,0.1

Type RM Length L Ch R = 1 ,2843    ,312.7,312.7,312.7
BEGIN DESCRIPTION:
Structure
END DESCRIPTION:
XS GIS Cut Line= 5
2308487.43984397725400.5061199452308179.33550749725465.614001357
2307894.83946836725588.6217674762307813.89580292725877.867275553
2307398.91335322726291.883224168
#Sta/Elev= 30
       0 2175.11      32 2168.32    68.8 2154.02   117.4 2147.96   146.4 2136.26
   228.2 2113.03   290.2 2102.58   364.2 2084.44   411.3 2078.33   527.5 2049.48
   553.7 2045.48   606.1 2042.67   630.7 2029.49   662.8 2029.38   679.4 2024.18
   708.5 2020.48   725.1 2018.56   916.8 2022.38   925.2 2025.05   946.9 2041.36
   957.1 2046.53   988.2 2050.18  1043.2 2065.66  1085.9 2070.12  1167.8 2085.47
  1225.8 2090.41    1278  2098.1  1424.9 2134.98  1467.9 2152.85  1511.4 2166.85
#Mann= 6 ,-1,0
       0      .1       0  494.91     .06       0   708.5    .045       0
   725.1     .06       0  894.86     .05       0 1375.22      .1       0
Bank Sta=708.5,725.1
XS Rating Curve= 0 ,0
Exp/Cntr(USF)=0,0
Exp/Cntr=0.3,0.1

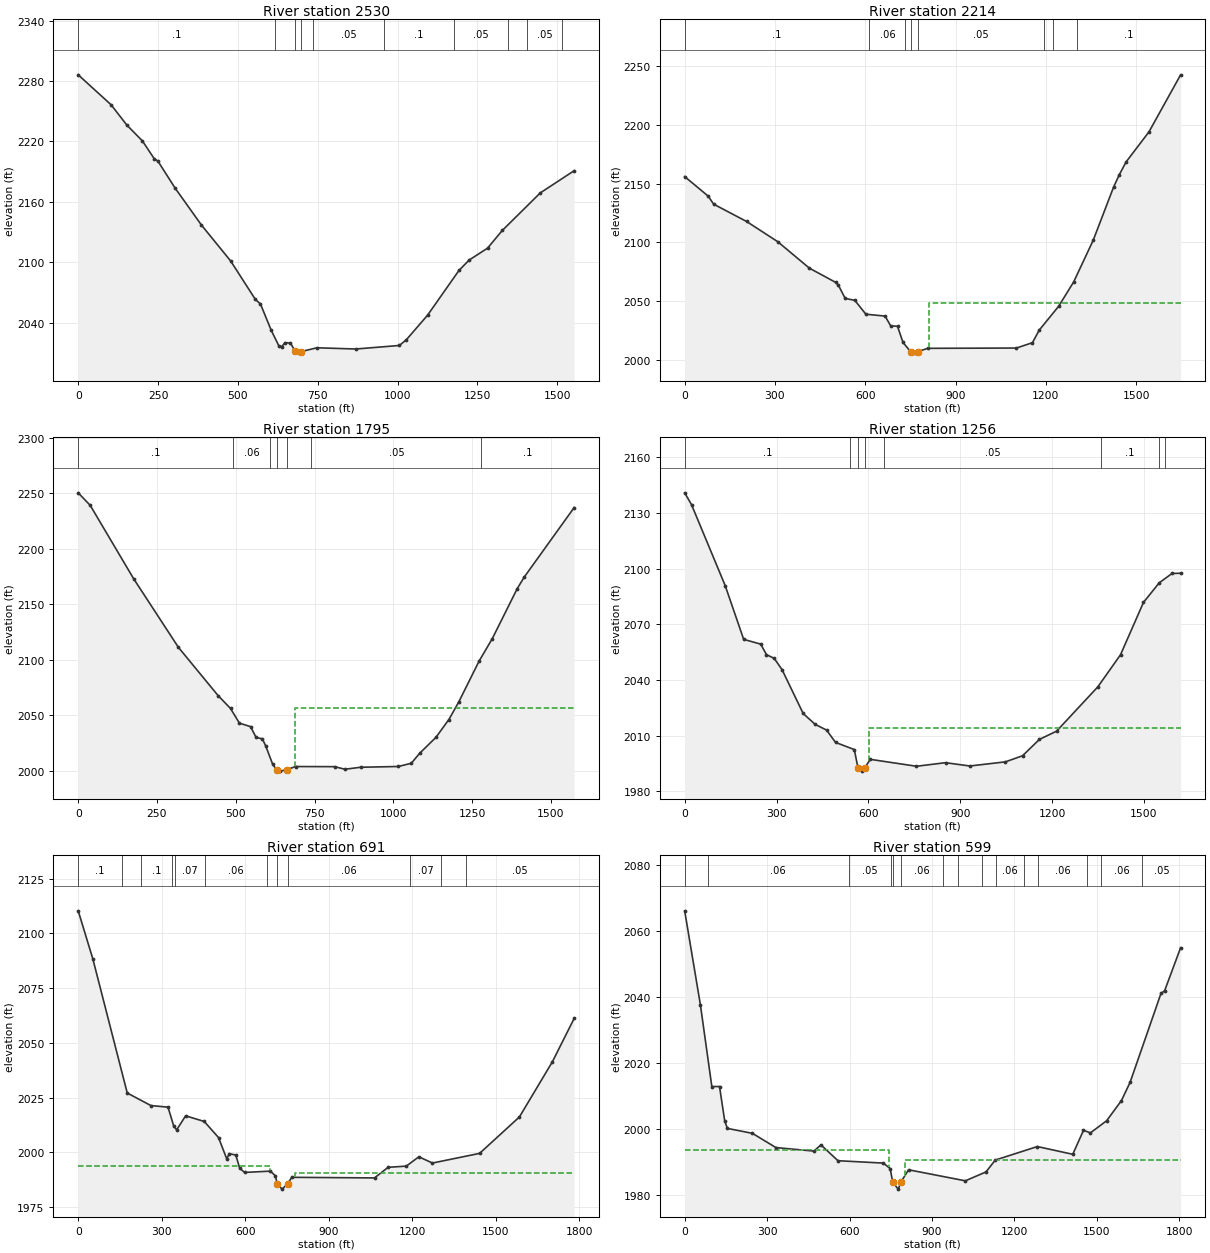
Type RM Length L Ch R = 1 ,2530    ,316.1,316.1,316.1
XS GIS Cut Line= 3
2308228.71323067725135.4654189832307675.59169978725406.382087172
2307229.70801672726230.420286248
#Sta/Elev= 30
       0 2286.06     103 2256.32     152 2236.25     201 2220.44   237.9 2202.83
   249.4 2200.43   303.6 2173.49   385.8  2136.9   477.2 2101.28   554.8    2063
   570.7  2058.5   604.1 2032.52   628.2  2016.9   637.3 2016.11   647.1 2020.09
   664.6 2019.76   679.5 2011.35   690.3 2009.71   698.7 2011.29   747.4 2015.02
   869.2  2013.8  1005.7 2017.32  1027.8 2023.14  1093.8 2047.35  1192.1  2091.8
    1224 2102.14  1281.6 2113.93  1327.9 2131.55  1446.8 2168.81  1552.8 2190.87
#Mann= 10 ,-1,0
       0      .1       0  615.91     .06       0   679.5    .045       0
   698.7     .06       0  735.91     .05       0  955.91      .1       0
 1175.91     .05       0 1345.91      .1       0 1405.91     .05       0
 1515.91      .1       0
Bank Sta=679.5,698.7
XS Rating Curve= 0 ,0
Exp/Cntr(USF)=0,0
Exp/Cntr=0.3,0.1

Type RM Length L Ch R = 1 ,2214    ,418.5,418.5,418.5
XS GIS Cut Line= 3
  2307905.663331724835.5767389022307488.00013421725098.309466072
2306927.25907203726107.474055076
#Sta/Elev= 30
       0 2156.06    78.1 2139.41    96.3 2132.55   205.8 2117.78   308.9 2100.62
   414.2 2078.04   501.3 2065.94   510.4 2063.68   533.3 2052.21   565.4 2050.58
     602 2038.76     666 2037.16   684.3  2028.9   707.2 2028.44   725.5 2014.65
  750.452006.917   766.7 2005.59   775.8 2006.94   807.2 2009.68  1102.5 2009.93
  1155.7 2014.52  1177.8 2025.11  1242.5 2045.47  1292.6  2066.3  1357.3  2101.7
  1424.9 2146.91  1443.9 2157.54  1466.8 2168.58  1542.6 2194.13  1647.9 2242.79
#Mann= 8 ,-1,0
       0      .1       0  613.43     .06       0  733.43     .05       0
  750.45    .045       0   775.8     .05       0 1193.43      .1       0
 1223.43     .05       0 1303.43      .1       0
#XS Ineff= 2 , 0
                             813         2048.58
Permanent Ineff=
       F       F
Bank Sta=750.45,775.8
XS Rating Curve= 0 ,0
Exp/Cntr(USF)=0,0
Exp/Cntr=0.3,0.1

Type RM Length L Ch R = 1 ,1795    ,538.8,538.8,538.8
XS GIS Cut Line= 2
2307299.86478275724587.9506919732306527.77473093725959.733819274
#Sta/Elev= 30
       0 2250.53    38.1 2239.22   175.8  2173.1   318.1 2111.12   444.2 2067.55
   483.4 2056.02   511.7 2042.76     547 2039.62   564.6 2029.83   584.3 2028.66
   594.7 2022.54   617.4 2005.54   630.2 2000.65   640.9 1999.48  661.52 2000.74
   689.9 2003.62   813.8 2003.51   846.5 2001.17   896.4 2002.97  1015.8 2003.66
  1057.1 2006.54  1084.4 2015.76  1135.2 2029.88  1176.5 2046.04  1207.8 2061.86
  1272.4 2098.74  1314.2 2118.97  1392.8 2163.77  1415.1 2174.31  1574.1 2237.25
#Mann= 7 ,-1,0
       0      .1       0     490     .06       0     610      .1       0
   630.2    .045       0  661.52      .1       0     740     .05       0
    1280      .1       0
#XS Ineff= 2 , 0
                          687.39         2056.22
Permanent Ineff=
       F       F
Bank Sta=630.2,661.52
XS Rating Curve= 0 ,0
Exp/Cntr(USF)=0,0
Exp/Cntr=0.3,0.1

Type RM Length L Ch R = 1 ,1256    ,565.2,565.2,565.2
BEGIN DESCRIPTION:
Structure XS 4
END DESCRIPTION:
XS GIS Cut Line= 2
2306836.78053911724355.2030250442306013.87115949725750.339204757
#Sta/Elev= 30
       0 2140.94    22.3 2134.57   132.3  2090.9   192.7 2061.91   248.4 2059.34
     267  2053.7   292.5 2051.63   318.1 2045.54     387 2021.93   426.3 2016.05
   463.4 2012.99   492.6 2006.35     554 2002.48  566.271992.344   578.1 1990.85
  587.411992.406     606 1997.21     757 1993.47   851.9  1995.4   931.1 1993.62
  1047.6 1995.85  1103.5 1999.15  1158.6 2007.97  1214.4 2012.38  1349.1 2036.26
  1423.4  2053.6  1498.4 2081.85    1550 2092.43  1591.6 2097.45  1619.7 2097.58
#Mann= 8 ,-1,0
       0      .1       0     540     .06       0  566.27    .045       0
  587.41     .06       0     650     .05       0    1360      .1       0
    1550     .05       0    1570      .1       0
#XS Ineff= 2 , 0
                          602.37         2014.19
Permanent Ineff=
       F       F
Bank Sta=566.27,587.41
XS Rating Curve= 0 ,0
Exp/Cntr(USF)=0,0
Exp/Cntr=0.5,0.3

Type RM Length L Ch R = 1 ,691     ,92,92,92
BEGIN DESCRIPTION:
Structure XS 3 28.1ft
END DESCRIPTION:
XS GIS Cut Line= 6
2306500.28677893724314.3362651132306326.81544983724283.604155565
2306084.51435472724701.9164235412305752.80342118  725115.9902391
 2305700.3819015725313.891621114 2305519.2060106 725739.84839199
#Sta/Elev= 30
       0 2110.29    52.7 2088.27   176.2 2027.11   261.2 2021.38   322.7 2020.66
   343.2 2012.09   353.7 2010.27     386  2016.7   452.8 2014.13   504.2 2006.78
   533.5 1997.12   543.2  1999.4   566.3  1998.8   580.3 1992.78   597.9 1990.85
   690.9 1991.45   708.1 1989.34  715.811985.618   732.7 1983.23   752.4 1985.64
   767.2 1988.62  1064.8 1988.35  1113.7 1993.19    1179 1993.73    1224 1997.99
    1273 1995.14  1442.4 1999.55  1585.6  2016.2  1703.7 2041.31  1782.2 2061.16
#Mann= 12 ,-1,0
       0      .1       0  156.46     .06       0  226.21      .1       0
  336.21     .06       0  346.21     .07       0  456.21     .06       0
  679.63      .1       0  715.81    .045       0   752.4     .06       0
  1191.3     .07       0 1304.39     .06       0 1394.39     .05       0
#XS Ineff= 2 , 0
          687.71  1993.8   780.5          1990.8
Permanent Ineff=
       F       F
Bank Sta=715.81,752.4
XS Rating Curve= 0 ,0
Exp/Cntr(USF)=0,0
Exp/Cntr=0.5,0.3

Type RM Length L Ch R = 1 ,599     ,111.1,111.1,111.1
BEGIN DESCRIPTION:
Structure XS 2 44.5ft 14.83
END DESCRIPTION:
XS GIS Cut Line= 6
2306420.30615724724245.6888519652306266.48525604724213.319206759
2306015.99648264724651.2819026282305684.68214381725065.261628295
2305671.42243346   725299.1675942305475.97014507725742.126235318
#Sta/Elev= 30
       0 2066.01    57.2 2037.61    98.8 2012.89   126.8  2012.9   145.8 2002.45
   155.5 2000.24   246.7 1998.74   332.1 1994.44   470.4 1993.38   495.9 1995.26
   557.9 1990.47   723.2 1989.75   747.9  1988.1   757.3  1983.9   777.4 1981.88
   786.2 1983.91   814.8 1987.73  1021.4 1984.39  1096.7 1987.08  1130.3 1990.66
  1283.5 1994.75  1412.5 1992.41  1451.5 1999.66  1476.8 1998.89  1535.8 2002.56
  1589.5 2008.63  1621.2 2014.18  1733.8  2041.1  1746.5 2041.79    1805 2054.86
#Mann= 15 ,-1,0
       0      .1       0   83.54     .06       0   597.2     .05       0
  751.74     .06       0   757.3    .045       0   786.2     .06       0
  941.74     .05       0  993.41     .06       0 1083.41     .05       0
 1133.41     .06       0  1236.5     .07       0  1286.5     .06       0
  1464.6     .05       0  1514.6     .06       0  1664.6     .05       0
#XS Ineff= 2 , 0
          742.47  1993.8  801.03          1990.8
Permanent Ineff=
       F       F
Bank Sta=757.3,786.2
XS Rating Curve= 0 ,0
Exp/Cntr(USF)=0,0
Exp/Cntr=0.5,0.3

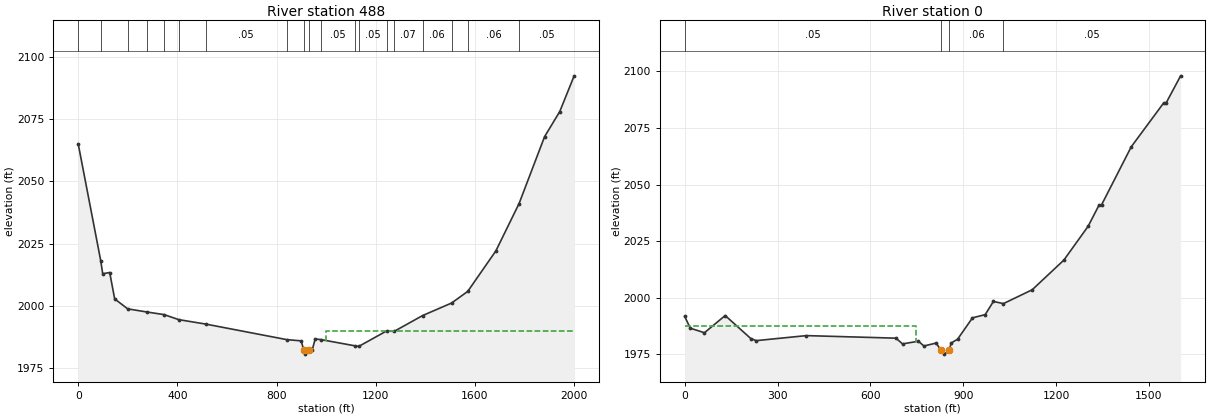
Type RM Length L Ch R = 1 ,488     ,488.1,488.1,488.1
XS GIS Cut Line= 6
2306434.49631057724200.0306276992306222.79679086724178.267125672
2305836.98925494724696.6341739322305848.86025605724819.301185353
2305644.29240453 725049.060427962305436.55181728725718.256527137
#Sta/Elev= 30
       0 2065.04    90.8 2018.17    98.8 2012.93     127 2013.41   147.1 2002.83
   199.4 1998.83   276.3 1997.58   346.1 1996.52   405.9 1994.49   514.1 1992.72
   840.3 1986.49   899.7 1985.97  909.111982.438   915.8 1980.65     932 1982.39
   943.9 1982.29     956 1986.75   979.7 1986.47  1117.2 1983.97  1131.4 1983.74
  1244.7 1989.99    1274 1989.76  1389.2 1996.13  1506.3 2001.17  1571.3 2005.84
  1684.9 2022.11  1778.4  2041.1  1881.4 2067.97  1942.6 2078.05  2000.6 2092.38
#Mann= 19 ,-1,0
       0      .1       0    90.8     .06       0   199.4      .1       0
   276.3     .06       0   346.1     .05       0   405.9     .06       0
   514.1     .05       0   840.3     .06       0  909.11    .045       0
     932     .06       0   979.7     .05       0  1117.2     .06       0
  1131.4     .05       0  1244.7     .06       0    1274     .07       0
  1389.2     .06       0  1506.3     .05       0  1571.3     .06       0
  1778.4     .05       0
#XS Ineff= 2 , 0
       0                    1000       0    1990
Permanent Ineff=
       F       F
Bank Sta=909.11,932
XS Rating Curve= 0 ,0
Exp/Cntr(USF)=0,0
Exp/Cntr=0.3,0.1

Type RM Length L Ch R = 1 ,0       ,452.6,452.6,452.6
XS GIS Cut Line= 3
2305112.58992976724279.0980923042305582.85650469 725300.80821044
2305393.78067184725739.526274389
#Sta/Elev= 30
       0 1991.76    18.1 1986.54    63.9 1984.53   130.9 1992.13   213.7 1981.96
   231.3 1981.04   393.3 1983.26   682.7 1982.13   703.9  1979.6   755.3 1980.78
   772.9 1978.68   812.5 1979.96  828.79 1976.73   838.9 1975.08   854.8 1976.75
   860.9 1979.97   881.8 1981.67     930 1991.12     971 1992.52   997.5 1998.34
    10301997.401  1122.8  2003.5  1225.3 2016.63  1303.6 2031.55  1338.6 2040.83
  1347.3 2041.09  1443.1  2066.7  1547.6 2086.02  1556.4 2086.22  1602.5 2098.02
#Mann= 4 ,-1,0
       0     .05       0  828.79    .045       0   854.8     .06       0
    1030     .05       0
#XS Ineff= 2 , 0
          746.36 1987.33
Permanent Ineff=
       F       F
Bank Sta=828.79,854.8
XS Rating Curve= 0 ,0
Exp/Cntr=0.3,0.1
LCMann Table=0

Chan Stop Cuts=-1
Use User Specified Reach Order=0
Composite Channel Slope=5